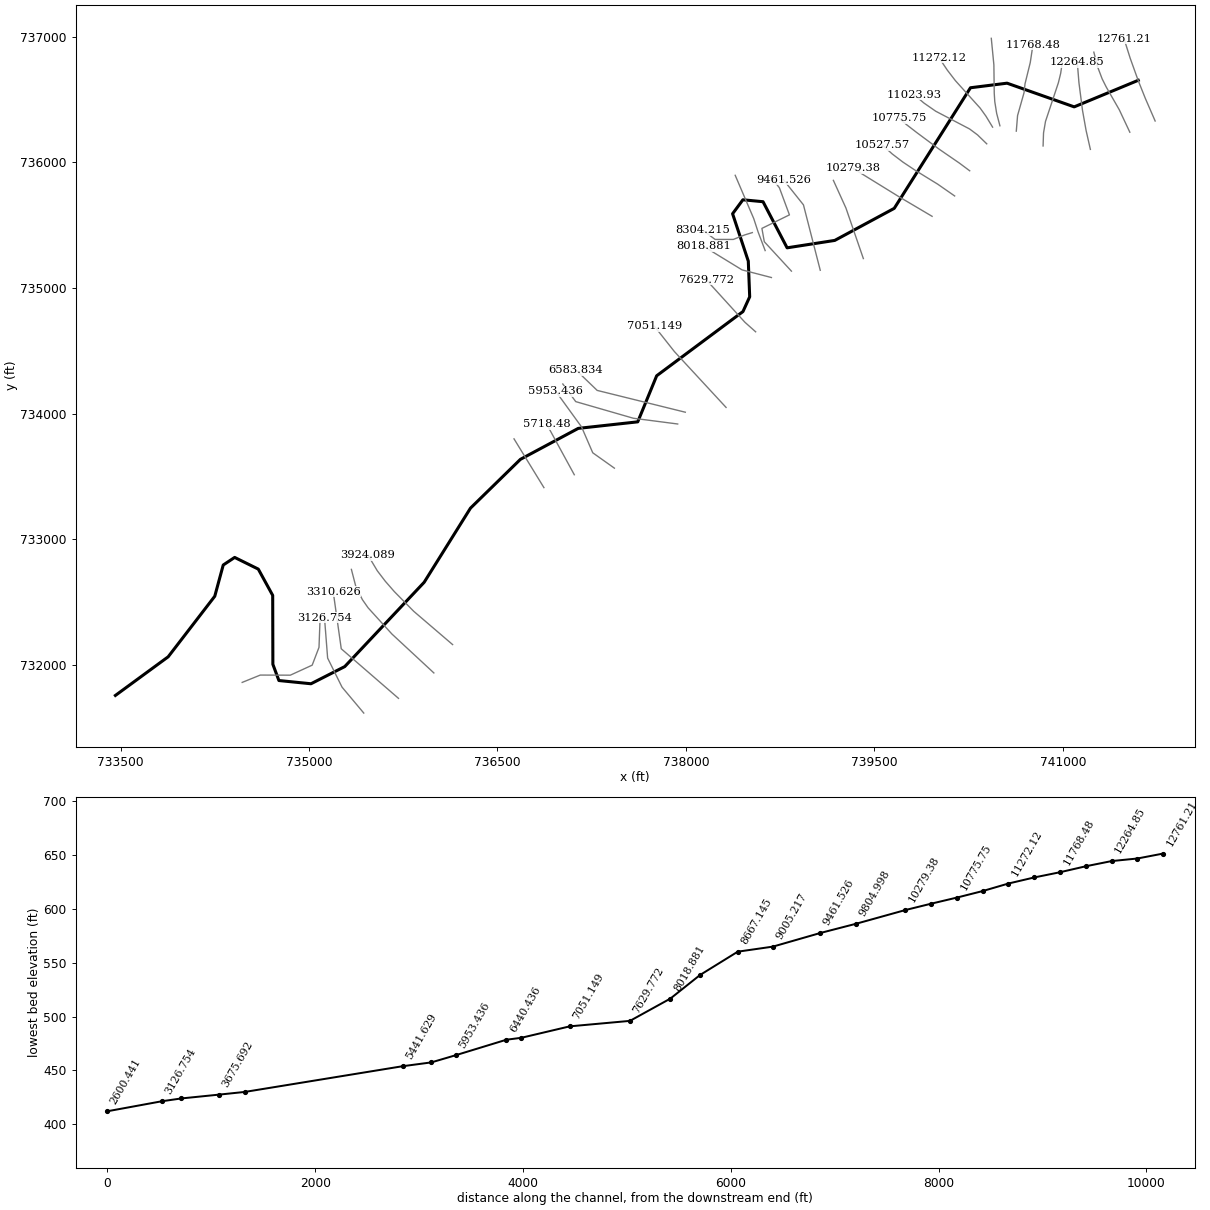
--- 4771_ras.prj (project) ---

Proj Title=4771
Current Plan=p01
Default Exp/Contr=0.3,0.1
English Units
Geom File=g01
Flow File=f01
Plan File=p01
Y Axis Title=Elevation
X Axis Title(PF)=Main Channel Distance
X Axis Title(XS)=Station
BEGIN DESCRIPTION:
RFD model 4771 exported to HEC-RAS
END DESCRIPTION:

--- 4771_ras.p01 (plan) ---

Plan Title=Plan 01
Program Version=4.10
Short Identifier=Plan 01
Geom File=g01
Flow File=f01
Subcritical Flow
Calc Critical at every XS
Secant Critical Depth

--- 4771_ras.f01 (steady flow) ---

Flow Title=Flow 01
Program Version=5.01
Number of Profiles= 6
Profile Names=10yr,25yr,50yr,100yr,100plus,500yr
River Rch & RM=4771,29,12761.21
 4940.8610003.2215961.8222807.0930214.95 50255.8
River Rch & RM=4771,29,12513.03
 4948.4510016.07 15978.422830.3430245.7550290.63
River Rch & RM=4771,29,12264.85
  4989.210084.9616067.1622954.84 30410.750476.96
River Rch & RM=4771,29,12016.66
 5078.3610235.3516260.5523226.05   3077050881.73
River Rch & RM=4771,29,11768.48
 5084.3710245.4816273.5523244.2930794.1650908.89
River Rch & RM=4771,29, 11520.3
 5107.6210284.6316323.7923314.7330887.4851013.75
River Rch & RM=4771,29,11272.12
 5112.2810292.4616333.8423328.8230906.1451034.71
River Rch & RM=4771,29,11023.93
 5260.9910542.1116653.31 23776.731499.4951698.92
River Rch & RM=4771,29,10775.75
 5269.83 10556.9 16672.223803.1631534.5651738.05
River Rch & RM=4771,29,10527.57
 5297.4610603.14 16731.223885.8531644.11 51860.2
River Rch & RM=4771,29,10279.38
  5313.510629.9716765.41 23933.831707.6351930.96
River Rch & RM=4771,29,9804.998
 5337.87 10670.716817.3124006.5431803.9952038.22
River Rch & RM=4771,29,9461.526
 5347.2910686.4416837.3624034.6431841.2252079.63
River Rch & RM=4771,29,9005.217
 5357.2810703.1116858.5824064.3831880.6252123.45
River Rch & RM=4771,29,8667.145
 5377.8110737.3916902.2124125.5231961.6152213.45
River Rch & RM=4771,29,8304.215
 5461.8410877.4317080.1624374.8632291.9452579.79
River Rch & RM=4771,29,8018.881
 5470.2110891.3517097.8324399.6132324.74 52616.1
River Rch & RM=4771,29,7629.772
 5479.1410906.2117116.6824426.0132359.7152654.81
River Rch & RM=4771,29,7051.149
 5489.4710923.3917138.4724456.5432400.1652699.55
River Rch & RM=4771,29,6583.834
 9246.5716889.4624374.8134559.6845784.8466668.89
River Rch & RM=4771,29,6440.436
 9247.5416890.9424376.5334562.0745788.0266672.03
River Rch & RM=4771,29,5953.436
 9270.4316925.8824417.28 34618.845863.1766746.42
River Rch & RM=4771,29, 5718.48
 9274.9516932.7824425.3234629.9845877.9866761.09
River Rch & RM=4771,29,5441.629
 9283.0216945.0824439.6734649.9545904.4566787.27
River Rch & RM=4771,29,3924.089
 9285.2816948.5324443.6834655.5445911.8566794.59
Boundary for River Rch & Prof#=4771,29,1
Up Type= 0
Dn Type= 2
Boundary for River Rch & Prof#=4771,29,2
Up Type= 0
Dn Type= 2
Boundary for River Rch & Prof#=4771,29,2
Up Type= 0
Dn Type= 2
Boundary for River Rch & Prof#=4771,29,2
Up Type= 0
Dn Type= 2
Boundary for River Rch & Prof#=4771,29,2
Up Type= 0
Dn Type= 2
Boundary for River Rch & Prof#=4771,29,2
Up Type= 0
Dn Type= 2

--- 4771_ras.g01 (geometry) ---

Geom Title=4771
Program Version=4.10

River Reach=4771,29
Reach XY= 30
741600.401552767736654.080991834741090.505719423736442.622658506
740556.130719423736631.164325163 740264.98488608736594.705991834
739658.214052737735634.810158491739184.776552767735379.601825178
738805.537307829735320.683238581738613.960580498735687.729718685
738453.543913841735703.007496461738371.599469423735591.896385342
738496.599469423735214.813052028738507.710580498734930.785274252
738454.238358319734813.424163133737767.432802767734302.313052014
737616.738358289733935.646385357737143.127247214733883.563052028
736682.710580498733637.035274252736285.488358319733248.840829805
735916.738358319732658.563052028735284.793913871731987.729718685
735016.043913871731850.924163118734760.488358289731876.618607566
734712.571691632732005.785274237734711.182802737732554.396385342
734596.599469393732763.424163118734408.405024976  732856.4797187
734317.432802737732796.063052028734250.071691662732547.451940909
733879.238358319732065.507496476733459.099469423731757.868607566

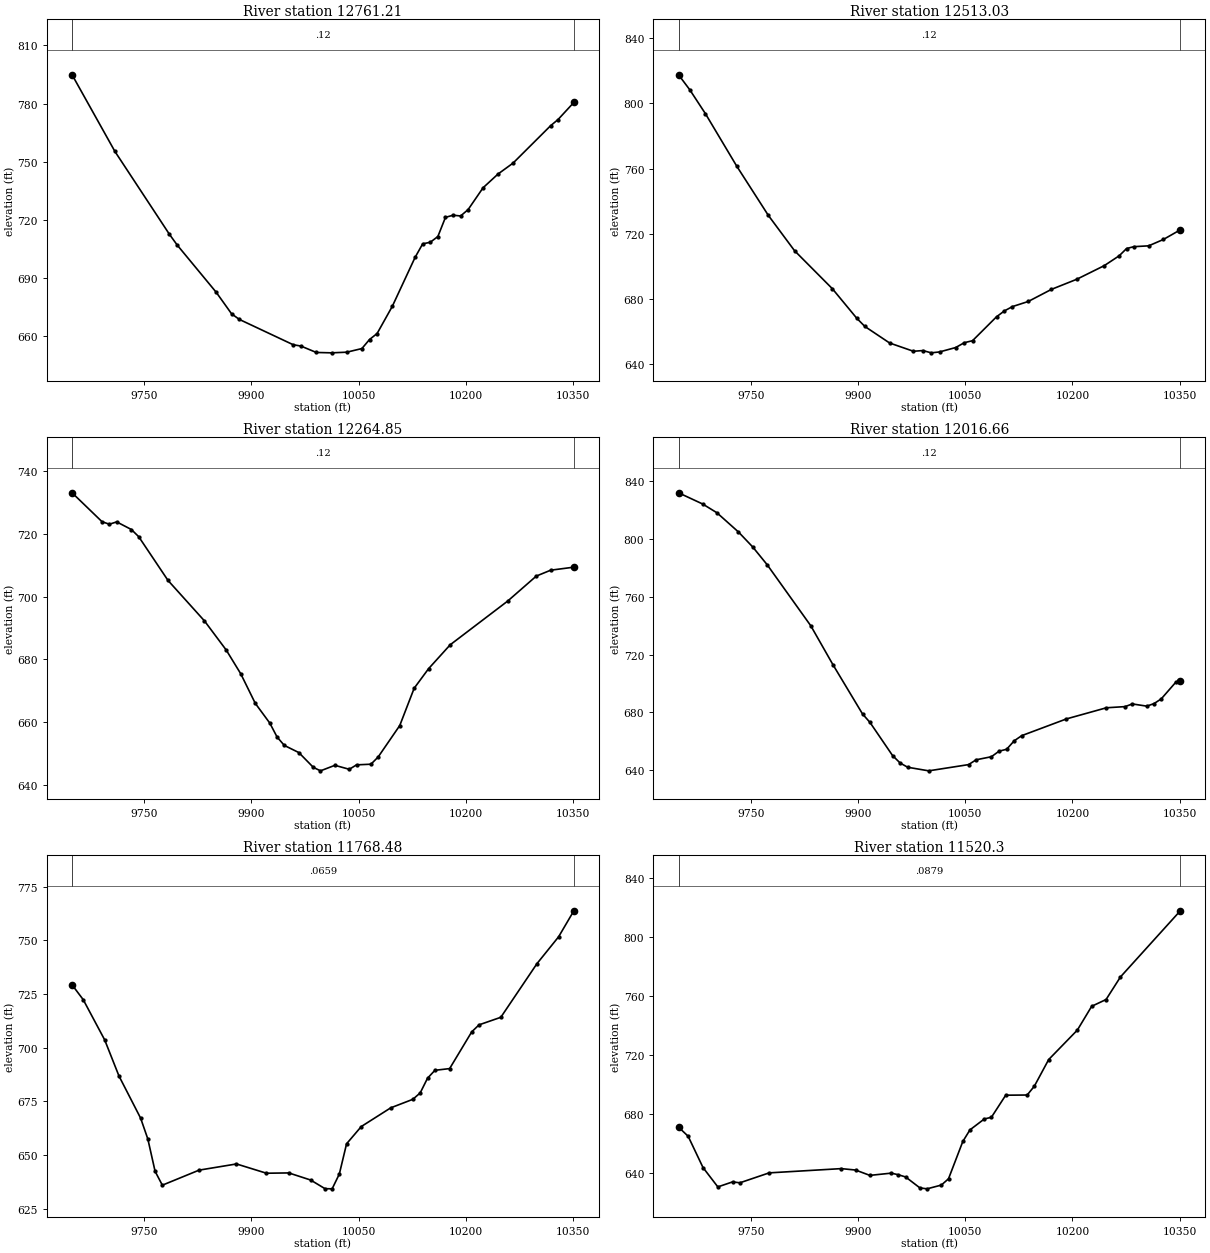
Type RM Length L Ch R = 1 ,12761.21,248.182800,248.182800,248.182800
XS GIS Cut Line= 6
 741734.95727883736329.991010626741656.843813289736509.860097888
 741602.15535097736646.592818011741599.113632582736654.665167833
741536.166757233736829.914688711741486.908217858736986.097143485
#Sta/Elev= 30
9649.011794.88019708.984755.3333  9785.3712.58699796.202707.04219850.645682.7559
9872.186671.63979882.956668.77239958.347655.71049969.118655.02989990.658651.7271
10011.98651.530910033.23 651.86210054.48653.745310065.11658.400910075.73661.4898
10096.99675.501610128.86700.737410139.49707.718810150.11708.531810160.74711.4985
10171.36721.372710181.99722.485910192.54  722.0910203.03725.3718   10224736.6413
10244.97743.734710265.94749.355610318.37768.592910328.86771.809610350.98780.6268
#Mann= 3 , 0 , 0
9649.011    0.12       09649.011    0.12       010350.98    0.12       0
#XS Ineff= 2 , 0
       0                               0
Bank Sta=9649.011,10350.98
Exp/Cntr=0.3,0.1

Type RM Length L Ch R = 1 ,12513.03,248.182700,248.182700,248.182700
XS GIS Cut Line= 6
741533.432642416736240.758177525741449.316436819  736419.7488832
741345.757351171736600.241297669741312.982371124736665.723451872
741278.288312993736757.466287483741246.917241266736878.081271339
#Sta/Elev= 30
9649.017817.5612 9664.65808.41969686.604793.70849730.512761.43289774.667731.2537
9811.253709.62579864.182686.2848 9898.35668.14599909.739663.09549944.284 652.968
 9977.61 647.8919990.871648.327610002.52646.930710014.11647.484910036.63650.1752
10048.86653.171410060.26 654.36810093.81669.042210104.99672.700810116.17675.3235
10138.21678.446210170.69685.8833   10206692.061310244.56700.4393 10265.4706.4775
10275.79710.944310286.08712.082810306.64712.594610327.21716.485610350.95722.4238
#Mann= 3 , 0 , 0
9649.017    0.12       09649.017    0.12       010350.95    0.12       0
#XS Ineff= 2 , 0
       0                               0
Bank Sta=9649.017,10350.95
Exp/Cntr=0.3,0.1

Type RM Length L Ch R = 1 ,12264.85,248.182700,248.182700,248.182700
XS GIS Cut Line= 6
741219.378149794736104.108735621741185.137209047736255.244111703
741156.308123784736417.300715116741152.274926993736449.445924189
741128.459568269736634.121721941741115.091636294 736797.34508029
#Sta/Elev= 30
9649.035732.99899690.963723.79089701.216722.9986 9711.47723.73639731.977721.3138
 9742.23719.03779783.244705.11259834.224692.24019864.695682.96329885.009675.4087
9905.323666.00929925.637659.72459935.794655.30439945.951 652.6239966.265650.3448
9986.444645.65969996.525644.535510016.68 646.29210036.85645.027810046.93646.4371
 10067.1646.644910077.18 648.93310107.43 658.95110127.59670.819710147.76  677.04
10178.01684.640410258.32698.532610298.45706.499310318.52 708.36810350.97709.3331
#Mann= 3 , 0 , 0
9649.035    0.12       09649.035    0.12       010350.97    0.12       0
#XS Ineff= 2 , 0
       0                               0
Bank Sta=9649.035,10350.97
Exp/Cntr=0.3,0.1

Type RM Length L Ch R = 1 ,12016.66,248.182700,248.182700,248.182700
XS GIS Cut Line= 6
740842.957168269736131.274971545740846.535060539736235.089386206
740862.214074111736326.971693918 740964.62535671736634.214264055
740982.943739231736709.313598167740998.105854463736811.545815765
#Sta/Elev= 30
9649.041831.68789682.766823.9439 9702.77817.87989732.846804.63019752.897794.2375
9773.082781.97469834.033739.87329864.883713.12789906.399679.00659916.878673.1205
9948.407650.28999959.001645.13539969.595642.1952    9999639.721410054.72644.0203
10065.38647.353110086.72 649.46510097.38653.291210108.02654.615510118.53660.4278
10129.05     66410191.67675.575710247.58683.261410273.65684.0584 10283.8685.9071
10304.05684.386510314.13686.133610324.21689.364710344.36700.749710350.96701.4108
#Mann= 3 , 0 , 0
9649.041    0.12       09649.041    0.12       010350.96    0.12       0
#XS Ineff= 2 , 0
       0                               0
Bank Sta=9649.041,10350.96
Exp/Cntr=0.3,0.1

Type RM Length L Ch R = 1 ,11768.48,248.182700,248.182700,248.182700
XS GIS Cut Line= 6
740629.771748271736249.418950534740639.877358424736373.433040078
740691.154015856736554.670768941740699.242059111736626.422309249
740740.868228236736795.132585911740762.225732315736936.181824672
#Sta/Elev= 30
9649.069729.26479664.651722.36859694.654703.63069714.711686.74889744.962667.1232
9755.076657.38229765.189642.35849775.328635.88199826.711642.89659879.059645.7804
9920.987641.45569952.174641.60059982.771638.286810002.81634.264610012.83634.1802
10022.91641.092210033.02655.172910053.59663.215110094.79 671.93610125.69675.9061
10135.99678.886310146.29685.763810156.59689.429310177.19690.232310208.09707.3535
10218.26 710.61410248.76714.140210299.36  739.1610329.59751.659310350.94763.7925
#Mann= 3 , 0 , 0
9649.069  0.0659       09649.069  0.0659       010350.94  0.0659       0
#XS Ineff= 2 , 0
       0                               0
Bank Sta=9649.069,10350.94
Exp/Cntr=0.3,0.1

Type RM Length L Ch R = 1 , 11520.3,248.182700,248.182700,248.182700
XS GIS Cut Line= 6
740499.382309154736292.069805623740473.476256108736390.844690666
740458.532140622736483.560158152740454.256789667736550.434717911
 740451.31669585736777.003889909740430.693881496736988.188764773
#Sta/Elev= 30
9649.037671.18699662.482665.00399683.278643.75969704.021630.63699724.592634.0325
9734.878633.4218 9775.77 640.1559876.626643.04439896.667642.07829916.698 638.453
9946.698639.98099956.698638.85639966.698 637.3829986.698629.95079996.698629.3231
 10016.7631.8895 10026.7 636.151 10046.7661.4515 10056.7669.332910076.71676.6992
10086.71677.887210106.72692.858810136.74692.979410146.76 698.96310166.82717.0366
10206.93737.032110226.99753.185610247.09757.768410267.23773.092910350.98817.9853
#Mann= 3 , 0 , 0
9649.037  0.0879       09649.037  0.0879       010350.98  0.0879       0
#XS Ineff= 2 , 0
       0                               0
Bank Sta=9649.037,10350.98
Exp/Cntr=0.3,0.1

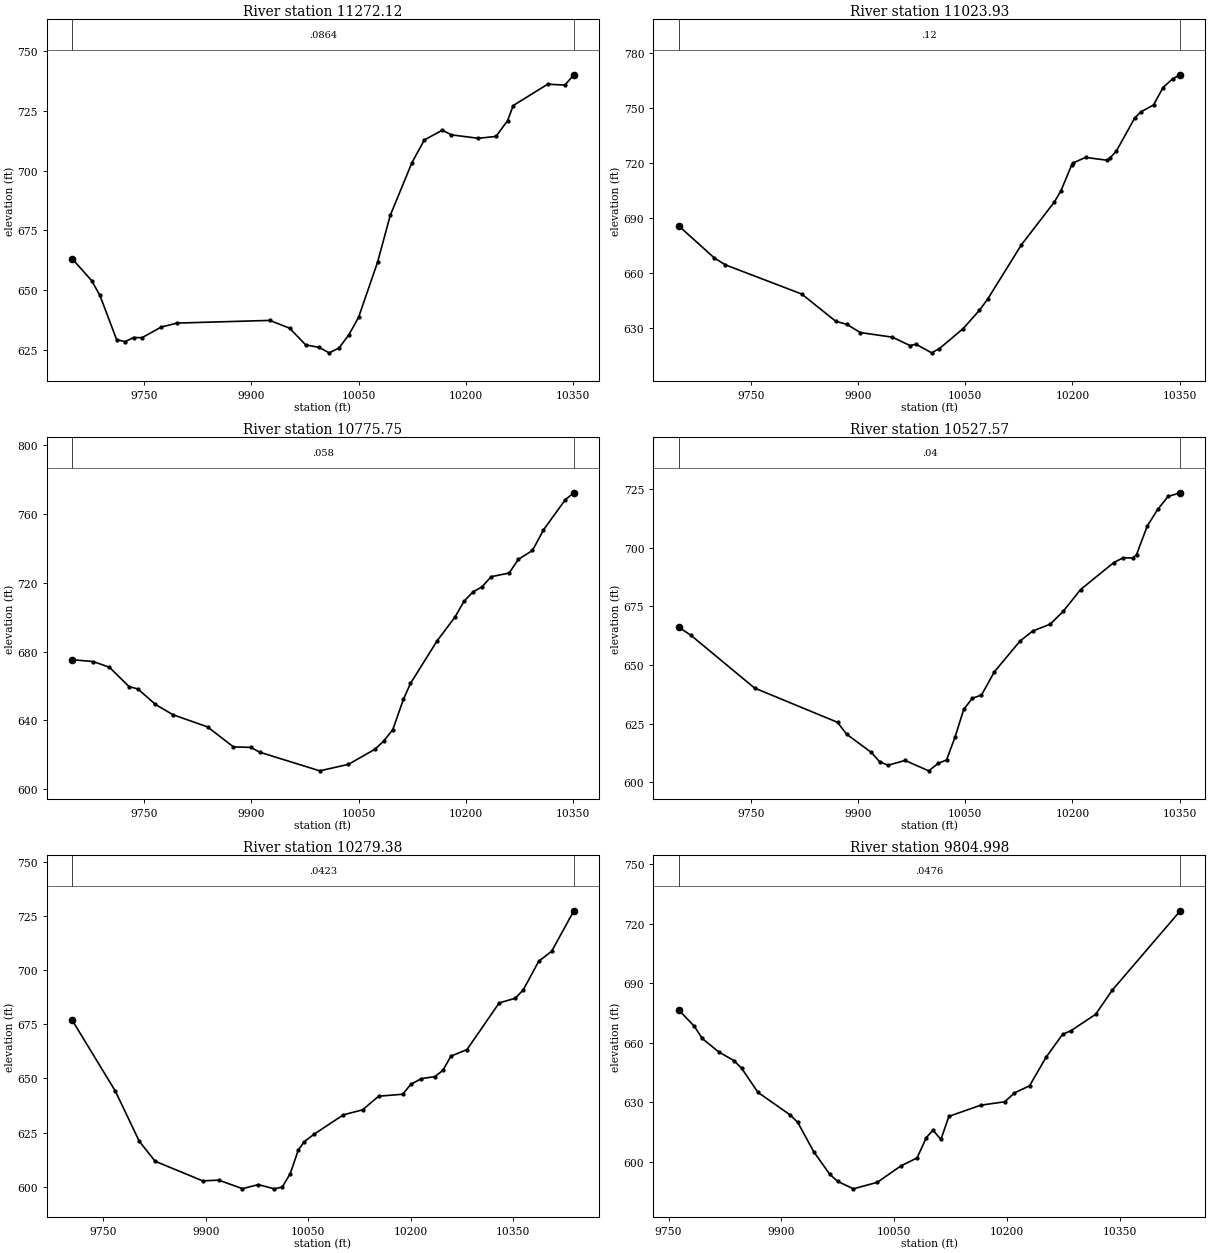
Type RM Length L Ch R = 1 ,11272.12,248.182800,248.182800,248.182800
XS GIS Cut Line= 6
740441.071032992736281.325603914740388.132391041736368.650586787
740342.297630393736432.441217327740145.004272038 736651.25729187
740080.771081344736734.951299106740013.353853231 736835.39052334
#Sta/Elev= 30
9649.047663.13979676.405653.9116 9687.96647.7578 9711.36629.22799723.195628.3613
 9735.03630.09899746.865630.01719773.691634.46339795.945636.1374 9925.62637.2568
9953.269634.00899975.832627.01019994.743 625.95210008.59623.679610022.42625.7074
10036.24631.228710049.83638.573610076.37661.617910094.06681.187110124.48703.3122
 10141.8712.814510167.02716.900110179.62714.936210217.44713.502810242.08714.2955
10258.28720.930610266.17 727.22610314.35736.155110338.44735.777410350.95740.0934
#Mann= 3 , 0 , 0
9649.047  0.0864       09649.047  0.0864       010350.95  0.0864       0
#XS Ineff= 2 , 0
       0                               0
Bank Sta=9649.047,10350.95
Exp/Cntr=0.3,0.1

Type RM Length L Ch R = 1 ,11023.93,248.182700,248.182700,248.182700
XS GIS Cut Line= 6
740394.399502973736148.549069974740321.130716328736219.598249313
740258.186735614736266.552162448739988.194532144736408.063411839
739894.645399328736473.065308637739816.912705088736539.191105608
#Sta/Elev= 30
9649.048685.82079699.133668.28369714.489664.54839821.421648.65339868.824633.8804
9884.613632.14619903.218627.71369948.072625.20689972.939620.61769981.179621.3706
10002.95616.677310013.96618.998610047.02629.801710069.91639.833610081.35645.8366
10128.59675.421310174.58698.639310184.05704.908610198.75 718.679 10201.5720.0554
10218.38722.970810248.42721.452710251.93722.454410261.27726.306710287.02744.3548
10296.08747.810310313.41751.489910326.77760.985210340.13765.742610350.93767.9279
#Mann= 3 , 0 , 0
9649.048    0.12       09649.048    0.12       010350.93    0.12       0
#XS Ineff= 2 , 0
       0                               0
Bank Sta=9649.048,10350.93
Exp/Cntr=0.3,0.1

Type RM Length L Ch R = 1 ,10775.75,248.182700,248.182700,248.182700
XS GIS Cut Line= 6
740258.802054555735933.832961207 740176.93494698735994.893370543
740013.161444193736107.608688002739836.396807184736239.007910346
739755.682712349736301.435801378739695.957387245736352.703714069
#Sta/Elev= 30
9649.023675.24299678.716674.15519701.153670.85599728.617 659.6379741.092658.2183
9765.642649.24339789.921643.27729838.479636.16239874.811624.52869899.176624.2576
9911.316621.47449995.483610.608210035.51614.3573 10072.9623.213410085.28628.0762
10097.66634.558110112.57652.221610122.43661.441110159.58 686.14810184.64700.0022
10197.28709.198210209.92714.668210222.56 717.59810235.21723.496810260.49725.6356
10273.17733.537110293.09738.746910308.45750.671110339.06768.312410350.98772.3019
#Mann= 3 , 0 , 0
9649.023   0.058       09649.023   0.058       010350.98   0.058       0
#XS Ineff= 2 , 0
       0                               0
Bank Sta=9649.023,10350.98
Exp/Cntr=0.3,0.1

Type RM Length L Ch R = 1 ,10527.57,248.182700,248.182700,248.182700
XS GIS Cut Line= 6
740139.033848651735733.497606178 740004.40902732  735827.1941139
739829.758866369735934.688183903739727.813856815736002.702085227
739642.076591885736068.037178917 739566.20402164736136.805552816
#Sta/Elev= 30
9649.021666.20959666.334662.71139755.383640.21499871.404625.61749884.166620.5501
9918.634612.78979930.442608.77899942.249607.31639965.864609.3636    9999604.9274
10012.12608.0817 10023.9609.549510035.92619.400610047.94631.097710059.96 635.852
 10072.8 637.23110090.81647.120210126.85660.297910144.64664.537610168.93667.4519
10186.98672.850610211.36682.168910257.91693.709910271.14695.750410284.37695.6392
10289.71697.094810304.76709.304810319.29716.347410333.82721.879810350.97723.4481
#Mann= 3 , 0 , 0
9649.021    0.04       09649.021    0.04       010350.97    0.04       0
#XS Ineff= 2 , 0
       0                               0
Bank Sta=9649.021,10350.97
Exp/Cntr=0.3,0.1

Type RM Length L Ch R = 1 ,10279.38,474.386600,474.386600,474.386600
XS GIS Cut Line= 3
739959.565605015735571.448854178739700.034000099735724.911020592
739331.968892783735952.059772491
#Sta/Elev= 30
9704.572676.89289767.963644.06029802.815 621.008 9826.05611.74489895.754602.6793
9918.989603.04449953.841599.09949977.076600.971910000.31 599.017   10012599.8379
10023.75 606.065 10035.5616.903610044.33620.8299   10059624.303810101.45 633.164
10129.51635.461210153.01641.745310188.26642.664810200.01647.2124 10215.7649.8775
10235.27650.778310247.02653.685610258.77660.234310282.27 663.27610329.27684.7621
10352.78686.943710364.53690.785610387.07703.966910406.11 708.61310438.59727.2991
#Mann= 3 , 0 , 0
9704.572  0.0423       09704.572  0.0423       010438.59  0.0423       0
#XS Ineff= 2 , 0
       0                               0
Bank Sta=9704.572,10438.59
Exp/Cntr=0.3,0.1

Type RM Length L Ch R = 1 ,9804.998,343.471600,343.471600,343.471600
XS GIS Cut Line= 3
739412.388865083735235.122279614739273.808493525735637.232538119
739173.848881274735857.598046988
#Sta/Elev= 30
9763.332676.58849784.357668.20629794.934662.08469816.701655.31499837.243650.8974
9847.392646.97499868.975634.90049911.284623.67469921.861619.78659943.015 605.061
 9964.17593.73289974.747590.09899995.901586.274110027.63589.565710059.36597.9121
10080.52601.850910092.92612.150110101.67615.862710112.25611.175410122.83622.8076
10165.14628.447310197.18 630.17810209.98634.621910230.12  638.2310252.08652.6274
10274.05 664.17410285.03665.976510317.97674.263610339.93686.369310430.63726.4837
#Mann= 3 , 0 , 0
9763.332  0.0476       09763.332  0.0476       010430.63  0.0476       0
#XS Ineff= 2 , 0
       0                               0
Bank Sta=9763.332,10430.63
Exp/Cntr=0.3,0.1

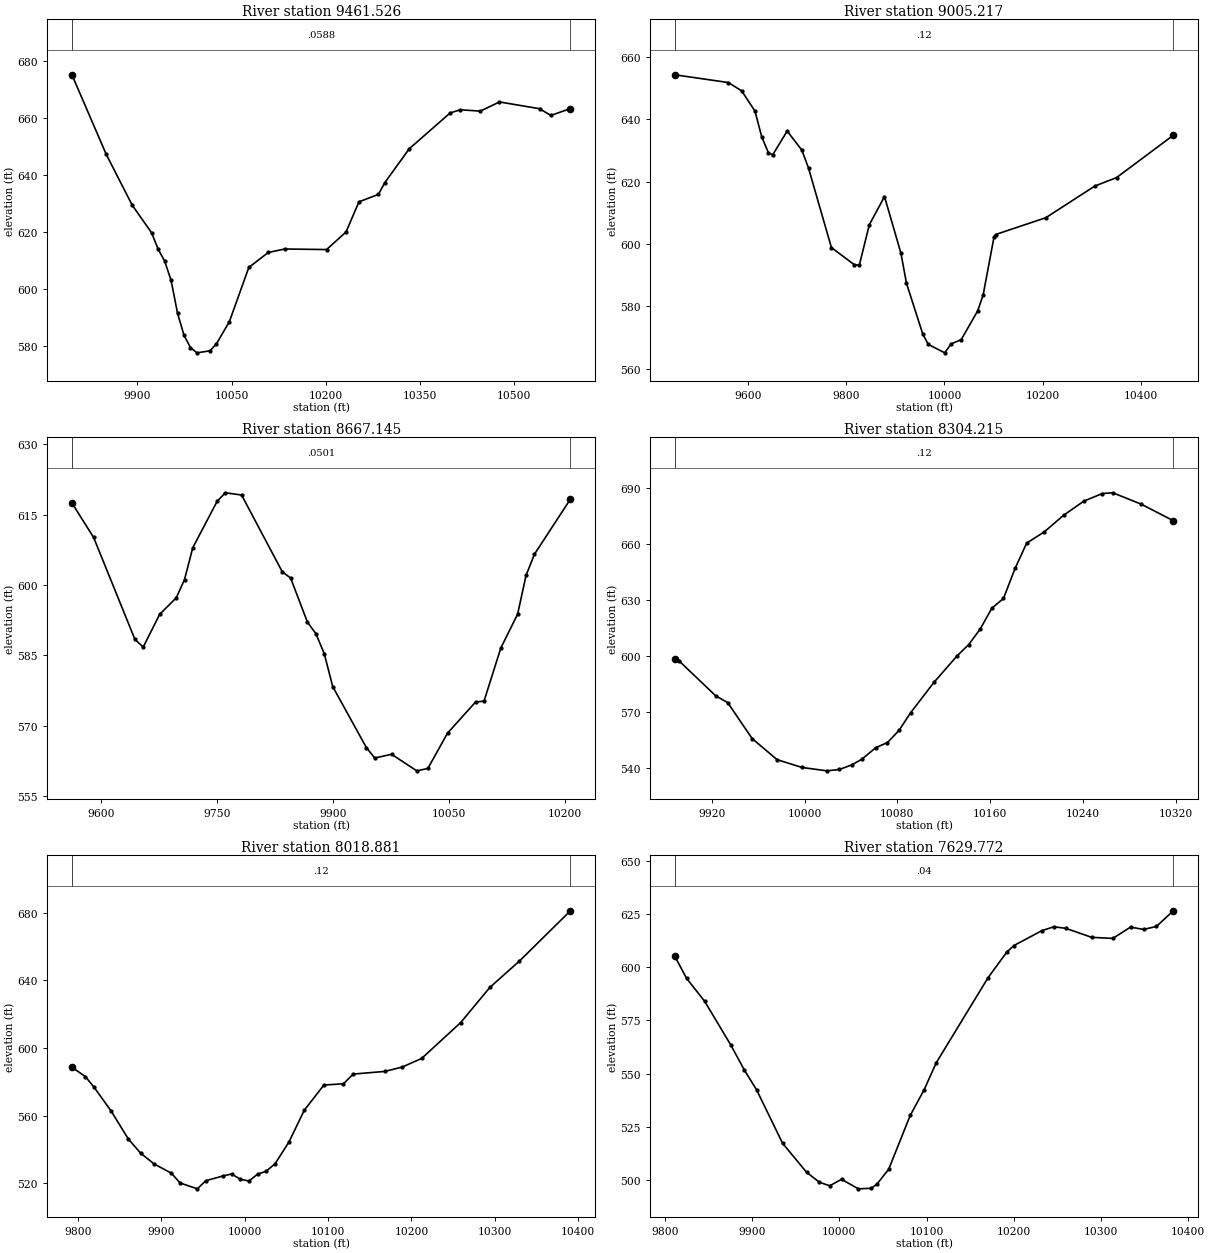
Type RM Length L Ch R = 1 ,9461.526,456.308900,456.308900,456.308900
XS GIS Cut Line= 3
739069.345650226735141.978095487738935.637525588735662.626284719
738775.563346684 735863.38229917
#Sta/Elev= 30
9795.594  675.069850.337647.18119891.635 629.4229922.608619.73139932.933614.0249
9943.257609.88529953.582603.12169963.906591.55619974.231583.84239984.555579.5338
 9994.88577.702510015.53578.410310025.85580.8238 10046.5 588.62510077.48607.6017
10108.45 612.83510134.69614.062710201.37613.864610232.34620.006410252.99630.5799
10283.97633.183110294.29637.338310333.14649.157310398.32661.705810414.36662.8061
10446.44662.332510476.86665.548910540.81663.176510558.72660.8237 10589.9663.2287
#Mann= 3 , 0 , 0
9795.594  0.0588       09795.594  0.0588       0 10589.9  0.0588       0
#XS Ineff= 2 , 0
       0                               0
Bank Sta=9795.594,10589.9
Exp/Cntr=0.3,0.1

Type RM Length L Ch R = 1 ,9005.217,338.072700,338.072700,338.072700
XS GIS Cut Line= 6
738839.892903894735135.162667364738624.071013719735369.159032449
738605.010374665735475.403681189738824.100655377735582.957091734
738744.431462407735798.063912794 738675.14667055735888.074924439
#Sta/Elev= 30
9451.819654.2942 9560.43651.81199587.638649.15729614.846642.6216 9628.45634.4185
9642.054629.28689650.781628.5933 9680.28636.22749710.074630.10889723.678624.3333
9770.148 598.8379816.721593.3299 9826.88593.1564  9847.2606.15169878.089615.1933
9911.497597.04239922.637587.45269956.057570.98839967.197567.740510000.62565.0427
10013.33567.901710034.04569.283610067.46578.5096 10078.6583.611810100.88602.3831
 10104.1603.026310205.94608.409510305.62618.5749 10349.9621.309510465.13634.8711
#Mann= 3 , 0 , 0
9451.819    0.12       09451.819    0.12       010465.13    0.12       0
#XS Ineff= 2 , 0
       0                               0
Bank Sta=9451.819,10465.13
Exp/Cntr=0.3,0.1

Type RM Length L Ch R = 1 ,8667.145,362.929200,362.929200,362.929200
XS GIS Cut Line= 5
738630.886441857   735298.732942738574.091207594735448.672360405
738540.014067024735553.175591409738460.450666696735738.799909458
738392.474599779735897.815351754
#Sta/Elev= 30
9562.003617.48299590.091610.11689643.558588.38189654.252586.72759675.638593.7393
9697.025597.23829707.718601.12879718.412607.91879750.031617.84459760.549619.6421
9781.585619.16149834.243602.80089845.122601.43969866.882592.03069877.762 589.601
9888.642585.29729899.522 578.3249943.042565.32099953.921563.07779975.681563.8783
10008.32560.348910022.67560.861310048.08568.378310084.46575.033710095.33575.2116
10117.09586.540710138.84593.766610149.71602.004310160.59606.538610207.15618.2827
#Mann= 3 , 0 , 0
9562.003  0.0501       09562.003  0.0501       010207.15  0.0501       0
#XS Ineff= 2 , 0
       0                               0
Bank Sta=9562.003,10207.15
Exp/Cntr=0.3,0.1

Type RM Length L Ch R = 1 ,8304.215,285.334600,285.334600,285.334600
XS GIS Cut Line= 5
738528.655020177735441.856932297738468.784000039735423.522131696
738377.117333382735387.411020577738232.672888964735387.411020577
738133.200915039735461.527393311
#Sta/Elev= 30
9888.193598.33639892.016597.49859923.391578.9147 9933.85 575.1799954.876555.9561
9976.372544.66819997.868540.478510019.36538.679710030.11539.416910040.86541.9091
10049.33544.876910061.45551.109710071.45 553.81410081.45560.343910091.45 569.815
10111.45586.010110131.45600.245210141.45606.307610151.45614.680810161.45625.8483
10171.45631.019210181.45647.113110191.45660.700210206.48666.628610223.21675.5636
10240.76683.194410256.69687.2479 10265.7687.654910290.16681.561310317.82672.6897
#Mann= 3 , 0 , 0
9888.193    0.12       09888.193    0.12       010317.82    0.12       0
#XS Ineff= 2 , 0
       0                               0
Bank Sta=9888.193,10317.82
Exp/Cntr=0.3,0.1

Type RM Length L Ch R = 1 ,8018.881,389.109200,389.109200,389.109200
XS GIS Cut Line= 3
738680.594201157735084.271285818 738447.48770377735144.818427995
738142.694193542735331.333859637
#Sta/Elev= 30
9792.547588.67219808.659583.11619818.991576.93539839.654562.73049860.318546.1951
9875.001537.85339891.313531.44539911.977526.01649922.309520.24669942.972516.7708
9953.304521.58619973.968524.3939  9984.3525.56979994.631522.445410004.96521.3874
 10015.3525.413210025.63527.192710036.31 531.58810052.89544.369610071.48563.3077
10094.92578.121710118.37578.8664 10130.1584.607410167.85586.162910188.71588.7284
10212.16593.823610259.06 615.04910294.23635.9166 10329.4651.339610390.72681.1245
#Mann= 3 , 0 , 0
9792.547    0.12       09792.547    0.12       010390.72    0.12       0
#XS Ineff= 2 , 0
       0                               0
Bank Sta=9792.547,10390.72
Exp/Cntr=0.3,0.1

Type RM Length L Ch R = 1 ,7629.772,578.622200,578.622200,578.622200
XS GIS Cut Line= 3
738555.112846802734652.238053941738469.709926039734728.151761293
 738162.02502653735066.225292876
#Sta/Elev= 30
9811.488605.09319825.019594.7453 9845.75 583.9829875.854563.37559890.906 551.962
9905.296 542.4389935.013517.42899962.465503.84089977.322499.09829989.099 497.473
10002.62500.502110021.89496.039910036.75496.307510043.19498.252810056.71505.2721
10081.32 530.46710097.27542.482410111.03555.084210170.46595.005610191.92607.0261
10200.18610.131210232.49617.188910246.01618.940810259.53618.233410289.32613.9918
10313.61613.495910333.89   618.810348.75617.6941 10363.6619.113410382.88626.4495
#Mann= 3 , 0 , 0
9811.488    0.04       09811.488    0.04       010382.88    0.04       0
#XS Ineff= 2 , 0
       0                               0
Bank Sta=9811.488,10382.88
Exp/Cntr=0.3,0.1

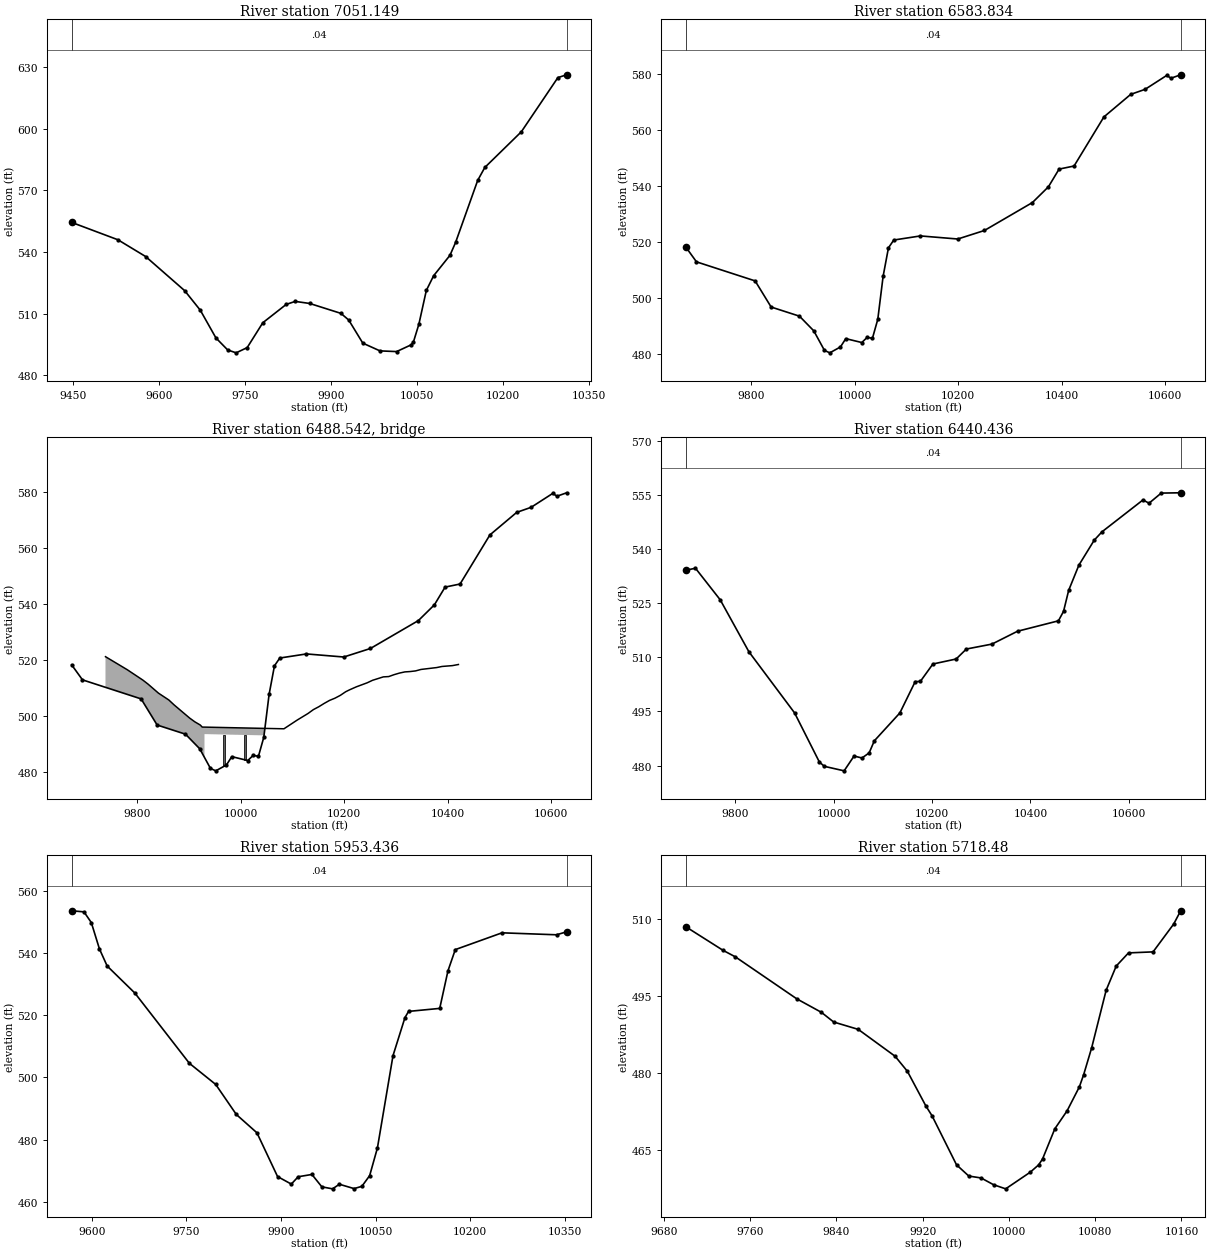
Type RM Length L Ch R = 1 ,7051.149,467.315800,467.315800,467.315800
XS GIS Cut Line= 3
738319.709926009734050.373983517737908.598814845734494.818427965
737748.784434885734697.002201751
#Sta/Elev= 30
9447.394 554.4519527.963546.00679576.295537.84749644.406521.2174 9671.65511.7036
9698.894498.2146 9719.41492.35819734.136 490.9639753.383493.51119780.627505.6131
9821.493514.55659837.223515.9992 9862.36515.00059916.848510.1815 9930.47506.9326
9955.036495.67929984.959491.914410013.94491.574110039.45494.8758 10043.4 496.332
10052.82504.9163 10065.8521.348110078.55528.5044   10107538.432310116.79544.6822
10155.38574.917510167.77581.201510231.51598.585210295.24624.962810310.54626.3286
#Mann= 3 , 0 , 0
9447.394    0.04       09447.394    0.04       010310.54    0.04       0
#XS Ineff= 2 , 0
       09841.076                       0
Bank Sta=9447.394,10310.54
Exp/Cntr=0.3,0.1

Type RM Length L Ch R = 1 ,6583.834,143.397900,143.397900,143.397900
XS GIS Cut Line= 3
737995.162415862734012.201713294737293.773526937734185.812824428
737125.497552186734347.856355622
#Sta/Elev= 30
 9673.93518.21599694.701512.87679808.021506.05679838.926496.70559893.672493.4305
 9921.34488.17459941.944481.17839952.246 480.3089972.849482.41679983.151485.3903
10014.06483.999110024.36485.826210034.66485.527310044.96492.305910055.26507.6965
10065.57517.898310075.87520.686310127.38522.154710199.49521.0529   10251524.1055
10343.71 534.10810374.62539.742410395.22 546.07910424.15547.180810481.81 564.755
10533.61572.828710561.38574.628410603.02579.595610611.56578.6173 10630.1579.8395
#Mann= 3 , 0 , 0
 9673.93    0.04       0 9673.93    0.04       0 10630.1    0.04       0
#XS Ineff= 2 , 0
       09913.224                       0
Bank Sta=9673.93,10630.1
Exp/Cntr=0.3,0.1

Type RM Length L Ch R = 3 ,6488.542,,,
BEGIN DESCRIPTION:
END DESCRIPTION:
Bridge Culvert--1,0,-1,-1, 0
Deck Dist Width WeirC Skew NumUp NumDn MinLoCord MaxHiCord MaxSubmerge Is_Ogee
60.544100,22.309700,2.6,0, 41, 41, , , 0.95, 0, 0,0,,
 9739.17 9781.19 9811.34 9821.39 9841.50 9861.60 9871.65 9901.80 9911.85 9922.24
 9926.07 9930.40 9930.4010046.5410046.5410083.9510109.6710130.4410140.8310151.22
10161.6110172.0010182.3910192.7810203.1710211.0510223.9410244.7210255.1110275.89
10286.2810296.6610307.0510317.4410327.8310338.2210348.6110379.2010389.2510409.34
10420.95
  521.17  516.51  512.79  511.35  508.12  505.66  503.92  499.19  497.84  496.71
  495.97  495.96  495.96  495.50  495.50  495.36  498.50  500.84  502.23  503.25
  504.44  505.52  506.31  507.32  508.62  509.34  510.39  511.82  512.72  513.94
  514.05  514.73  515.30  515.72  515.85  516.08  516.60  517.28  517.67  517.97
  518.37
 -478.83 -483.49 -487.21 -488.65 -491.88 -494.34 -496.08 -500.81 -502.16 -503.29
 -504.03 -504.04  493.46  493.00 -504.50 -504.64 -501.50 -499.16 -497.77 -496.75
 -495.56 -494.48 -493.69 -492.68 -491.38 -490.66 -489.61 -488.18 -487.28 -486.06
 -485.95 -485.27 -484.70 -484.28 -484.15 -483.92 -483.40 -482.72 -482.33 -482.03
 -481.63
 9739.17 9781.19 9811.34 9821.39 9841.50 9861.60 9871.65 9901.80 9911.85 9922.24
 9926.07 9954.71 9954.7110070.8510070.8510083.9510109.6710130.4410140.8310151.22
10161.6110172.0010182.3910192.7810203.1710211.0510223.9410244.7210255.1110275.89
10286.2810296.6610307.0510317.4410327.8310338.2210348.6110379.2010389.2510409.34
10420.95
  521.17  516.51  512.79  511.35  508.12  505.66  503.92  499.19  497.84  496.71
  495.97  495.86  495.86  495.41  495.41  495.36  498.50  500.84  502.23  503.25
  504.44  505.52  506.31  507.32  508.62  509.34  510.39  511.82  512.72  513.94
  514.05  514.73  515.30  515.72  515.85  516.08  516.60  517.28  517.67  517.97
  518.37
 -478.83 -483.49 -487.21 -488.65 -491.88 -494.34 -496.08 -500.81 -502.16 -503.29
 -504.03 -504.14  493.36  492.91 -504.59 -504.64 -501.50 -499.16 -497.77 -496.75
 -495.56 -494.48 -493.69 -492.68 -491.38 -490.66 -489.61 -488.18 -487.28 -486.06
 -485.95 -485.27 -484.70 -484.28 -484.15 -483.92 -483.40 -482.72 -482.33 -482.03
 -481.63
Pier Skew, UpSta & Num, DnSta & Num=  ,9968.61, 2 ,9992.92, 2 , 0 , 0 , 0 ,,
    3.00    3.00
 -504.19  495.81
    3.00    3.00
 -504.29  495.71
Pier Skew, UpSta & Num, DnSta & Num=  ,10008.33, 2 ,10032.64, 2 , 0 , 0 , 0 ,,
    3.00    3.00
 -504.35  495.65
    3.00    3.00
 -504.44  495.56
BR Coef=-1 , 0 , 0 ,, 0 ,,,0.8,0,1,0,
WSPro=,,,, 1 ,,,, 0 ,,,, 0 ,,,,-1 ,-1 ,-1 , 0 , 0 , 0 , 0 , 0
BC Design=,, 0 ,, 0 ,,,,,,

Type RM Length L Ch R = 1 ,6440.436,486.999300,486.999300,486.999300
XS GIS Cut Line= 4
737934.630008429733918.451713338737581.505008429733964.285046667
737123.171675116734096.576713324737020.387815148734236.907188743
#Sta/Elev= 30
9698.782534.19139718.576534.76359768.996525.98559827.348511.56599920.254 494.607
9970.673480.98199980.757 479.77110021.09478.519710041.26482.625410057.45482.0857
10072.05483.508210082.46 486.837 10134.5494.590810165.72503.292410176.13503.3275
10201.69508.172610248.99509.5605 10269.8512.329710321.84513.698710373.89517.2657
10457.15520.160510467.56522.793210477.97 528.61910498.78 535.62210530.01542.5518
10545.74544.863110629.12553.709110641.52552.809510666.31555.614210705.86555.7016
#Mann= 3 , 0 , 0
9698.782    0.04       09698.782    0.04       010705.86    0.04       0
#XS Ineff= 2 , 0
       09915.152                       0
Bank Sta=9698.782,10705.86
Exp/Cntr=0.3,0.1

Type RM Length L Ch R = 1 ,5953.436,234.956500,234.956500,234.956500
XS GIS Cut Line= 4
737430.821037114733567.040650174737258.598814875733689.262872413
737169.709926009733894.818427995736964.618640631734178.039726764
#Sta/Elev= 30
9568.028553.54059587.428553.19429599.059549.76569611.953541.28969624.215535.7822
9668.174527.08089754.568504.50689796.358497.70359829.042488.04939861.727482.1574
9894.412468.09239916.202465.67039927.097468.02999948.887468.76969964.641464.7812
9981.572 464.1449992.467465.617110015.73464.223310028.08464.948910040.43468.3817
10052.77477.306210077.47506.966610096.44519.210310102.16521.191610151.55 522.157
10164.64534.250210176.24 541.05710250.32546.455210336.75545.819710352.84546.7793
#Mann= 3 , 0 , 0
9568.028    0.04       09568.028    0.04       010352.84    0.04       0
#XS Ineff= 2 , 0
       0                               0
Bank Sta=9568.028,10352.84
Exp/Cntr=0.3,0.1

Type RM Length L Ch R = 1 , 5718.48,276.850600,276.850600,276.850600
XS GIS Cut Line= 2
737111.671146452733514.569811851 736891.91892615733917.448882431
#Sta/Elev= 30
9700.331508.41899734.994503.81699746.384502.55369803.339494.39139826.121491.7751
9837.511489.89059860.293 488.4599894.466483.23619905.857480.31199923.095473.5328
9928.638471.6979 9951.42462.13079962.811459.94889974.202459.57769985.745458.2656
9996.984457.463810019.77460.696810027.51462.115210031.16463.254110042.55469.1292
10053.94472.627310065.33477.288810069.28479.642510076.72484.873710090.16496.0741
 10099.5500.772110110.89503.325910133.67503.525410152.81508.943110159.25 511.513
#Mann= 3 , 0 , 0
9700.331    0.04       09700.331    0.04       010159.25    0.04       0
#XS Ineff= 2 , 0
       0                               0
Bank Sta=9700.331,10159.25
Exp/Cntr=0.3,0.1

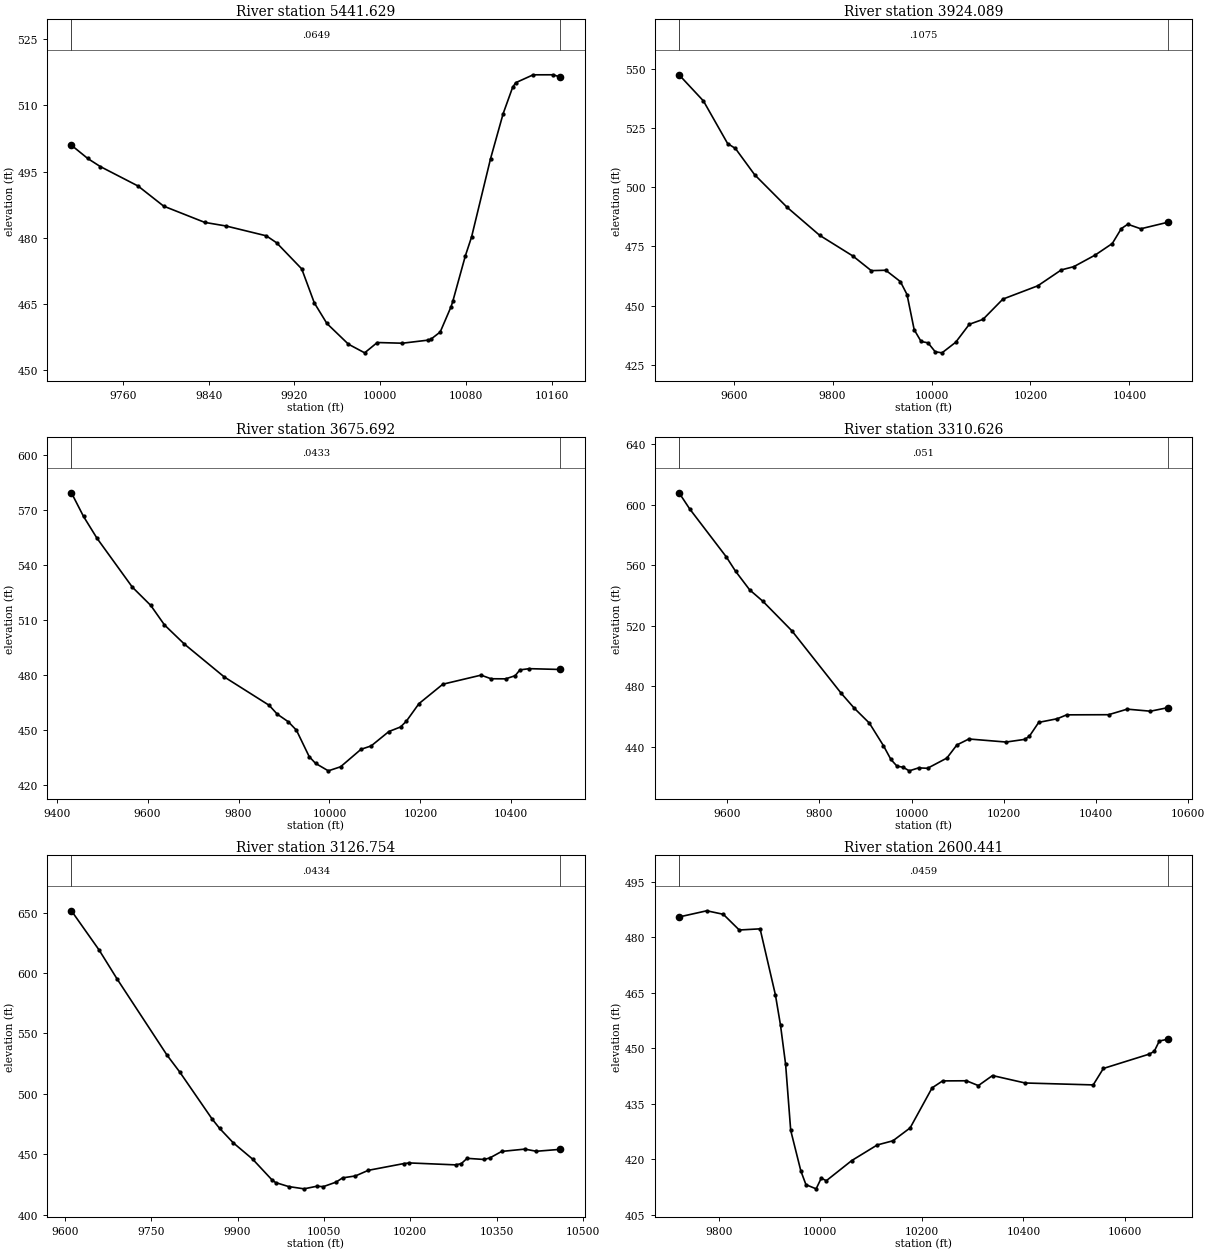
Type RM Length L Ch R = 1 ,5441.629,1517.540400,1517.540400,1517.540400
XS GIS Cut Line= 2
736869.943704069733412.018775702736631.878798723733800.247698262
#Sta/Elev= 30
9712.127500.97339727.354497.96669739.084 496.1359774.276491.72259798.102487.1644
9836.361483.48139856.389482.6541 9893.75 480.435 9903.31478.86689926.771472.9363
9938.501465.22619950.232460.55799970.268455.86699985.423453.90379997.153456.2426
10020.61456.085810044.07456.772110046.79456.929310055.81458.622410065.92464.3505
10067.54465.570610079.27475.907110085.05480.173510102.73497.913910114.46508.1186
 10123.3514.093210126.19515.151810142.43516.937710161.38516.946910167.53516.4207
#Mann= 3 , 0 , 0
9712.127  0.0649       09712.127  0.0649       010167.53  0.0649       0
#XS Ineff= 2 , 0
       0                               0
Bank Sta=9712.127,10167.53
Exp/Cntr=0.3,0.1

Type RM Length L Ch R = 1 ,3924.089,248.397200,248.397200,248.397200
XS GIS Cut Line= 6
736143.152494443732162.739458851735833.488725811732427.808897451
735679.545371771732584.131775737735607.418038338732666.766481444
735543.922003895732749.823664248735468.792416036732875.634613618
#Sta/Elev= 30
9489.483547.40439538.812536.35399587.705518.37789603.481516.29579642.319 505.218
9708.046 491.4469773.758479.6414 9841.16470.87349878.112464.72049907.481464.8827
9936.991460.10079950.435454.64159964.937439.78049978.909434.81319992.882434.2401
10007.43430.482410021.23430.020510048.83434.477910076.42442.076410104.02444.1426
10144.32452.712810214.78458.311410262.44465.032710287.62466.393910330.87471.2991
10365.48476.169710383.76482.477810396.78484.299910423.08482.389310477.52485.1331
#Mann= 3 , 0 , 0
9489.483  0.1075       09489.483  0.1075       010477.52  0.1075       0
#XS Ineff= 2 , 0
       0                               0
Bank Sta=9489.483,10477.52
Exp/Cntr=0.3,0.1

Type RM Length L Ch R = 1 ,3675.692,365.065500,365.065500,365.065500
XS GIS Cut Line= 6
 735994.02452615731937.032263576735659.976705164 732246.89411287
735470.308515817732455.673963889735425.341430545732520.068581447
735373.435403764 732622.53709884735337.548066258732761.254007965
#Sta/Elev= 30
 9432.36579.20879459.026566.29339488.708554.37969566.373527.73389606.973517.7365
9637.121507.10589681.009496.63459768.538478.75579867.374463.27219885.245458.4259
9909.376454.30959927.413449.68579955.453435.27739969.473431.59049997.512427.5129
10024.51429.729510069.44439.260110091.85441.119110130.72448.951610156.51451.4612
 10169.4454.661810197.01464.1968 10249.5474.775710333.57479.724110355.53 477.749
10387.62477.701510408.65479.423210419.04482.592910439.82 483.25210507.37 482.815
#Mann= 3 , 0 , 0
 9432.36  0.0433       0 9432.36  0.0433       010507.37  0.0433       0
#XS Ineff= 2 , 0
       0                               0
Bank Sta=9432.36,10507.37
Exp/Cntr=0.3,0.1

Type RM Length L Ch R = 1 ,3310.626,183.872300,183.872300,183.872300
XS GIS Cut Line= 3
735712.407786191731734.771157742735256.852230608732129.215602204
735192.963341773 732581.99337998
#Sta/Elev= 30
9495.625608.02039518.652597.36949598.018565.62099618.191   556.19648.745 543.768
9677.383536.22089740.407 516.6319847.346475.27929875.798465.37929908.454455.5239
9939.008440.57889955.164431.46759968.391427.03559981.619426.32369994.847423.9368
10015.39425.903110034.53425.6342 10076.5432.385910098.22441.072710124.26445.0244
10205.05443.000210245.45444.768710255.55446.868710275.74456.011310316.14458.4519
10336.34461.005310427.23461.095110467.63464.778510518.12463.417610555.48  465.75
#Mann= 3 , 0 , 0
9495.625   0.051       09495.625   0.051       010555.48   0.051       0
#XS Ineff= 2 , 0
       0                               0
Bank Sta=9495.625,10555.48
Exp/Cntr=0.3,0.1

Type RM Length L Ch R = 1 ,3126.754,526.312400,526.312400,526.312400
XS GIS Cut Line= 4
735435.933789762 731617.75276165735263.017123102731824.002761651
735148.433789731732055.252761632735123.433789732 732376.08609499
#Sta/Elev= 30
9611.265651.51929659.413619.02919690.544 595.1529777.316532.08049799.499518.0572
9855.613479.25249868.662 471.4719892.683 459.3749926.164 445.9459959.645428.8344
9966.038 426.5779988.561423.275210015.45421.373210037.77423.534710048.93423.1922
10071.25426.958210082.41430.456910104.73 432.04310127.05436.689210188.39442.2451
10198.42442.819410278.66441.209610288.69442.248910298.72446.621610328.81445.6627
10338.84447.0995 10358.9452.349410399.03454.251810419.09452.4736 10460.3454.0542
#Mann= 3 , 0 , 0
9611.265  0.0434       09611.265  0.0434       0 10460.3  0.0434       0
#XS Ineff= 2 , 0
       0                               0
Bank Sta=9611.265,10460.3
Exp/Cntr=0.3,0.1

Type RM Length L Ch R = 1 ,2600.441,0.000000,0.000000,0.000000
XS GIS Cut Line= 6
 734468.35429212 731861.66502333734612.374874563 731920.09479855
734851.365598262 731919.22032915735025.517123045731999.002761678
735079.683789728732140.669428293735088.017123102732361.502761648
#Sta/Elev= 30
9722.037485.46999776.695 487.1419809.163486.19029840.565481.95069881.579482.2644
9911.737464.4225 9921.79456.20869931.829445.63859941.829427.84179961.829 416.863
9971.829 413.1729991.891412.046710001.94414.927810011.97414.245910062.08419.6946
10112.13423.895310143.05425.024410176.89428.503310220.16439.323410240.84441.1964
10287.75441.230110311.19439.930510339.02442.640310403.25440.633110537.24440.1143
10557.25444.558410647.32448.421410657.32449.169410667.33451.960910683.85452.4604
#Mann= 3 , 0 , 0
9722.037  0.0459       09722.037  0.0459       010683.85  0.0459       0
#XS Ineff= 2 , 0
       0                               0
Bank Sta=9722.037,10683.85
Exp/Cntr=0.3,0.1